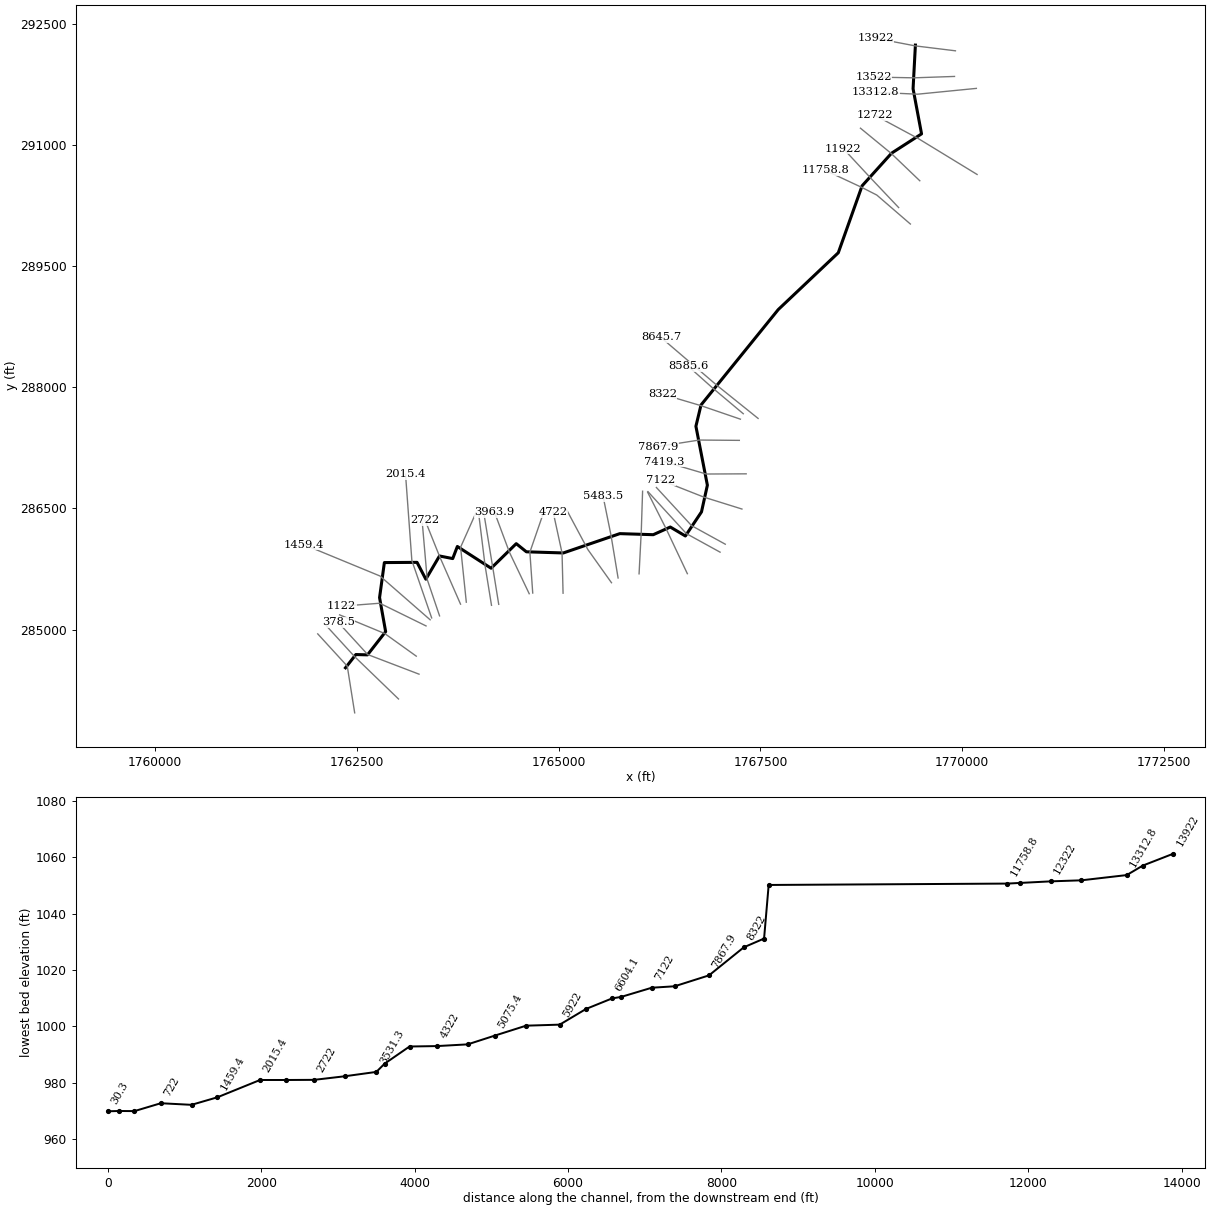
--- PedlerRn.prj (project) ---

Proj Title=PedlerRn
Current Plan=p01
Default Exp/Contr=0,0
English Units
Geom File=g01
Flow File=f01
Plan File=p01
BEGIN DESCRIPTION:
END DESCRIPTION:
DSS Export Rating Curves= 0
DSS Export Rating Curve Sorted= 0
DSS Export Volume Flow Curves= 0
DXF OffsetX= 0
DXF OffsetY= 0
DXF ScaleX= 0
DXF ScaleY= 0

--- PedlerRn.p01 (plan) ---

Plan Title=Floodplain
Program Version=4.00
Geom File=g01
Flow File=f01
K Sum by GR=0
Std Step Tol=0.01
Critical Tol=0.01
Num of Std Step Trials=20
Max Error Tol=0.3
Flow Tol Ratio=0.001
Split Flow NTrial=30
Split Flow Tol=0.02
Split Flow Ratio=0.02
Log Output Level=0
Friction Slope Method=1
Unsteady Friction Slope Method=2
Unsteady Bridges Friction Slope Method=1
Global Log Level=0
CheckData=False
Run HTab=0
Run UNet=0
Run PostProcess=0
UNET Theta=0
UNET Theta Warmup=0
UNET ZTol=0
UNET ZSATol=0
UNET MxIter=0
UNET MaxInSteps=0
UNET DtIC=0
UNET DtMin=0
UNET MaxCRTS=0
UNET WFStab=0
UNET SFStab=0
UNET WFX=0
UNET SFX=0
UNET DSS MLevel=0
UNET DZMax Abort=0
UNET Convert EG Bridges=0
UNET Use Existing IB Tables=0
UNET Froude Limit=0
UNET Froude Power=0
Write IC File=0
Echo Input=False
Echo Output=False
Write Detailed=0

--- PedlerRn.f01 (steady flow) ---

Flow Title=NFF Regression Equation
Program Version=4.00
Number of Profiles= 1
Profile Names=P100yr
River Rch & RM=PedlerRn,Main            ,13922
     722
River Rch & RM=PedlerRn,Main            ,12722
747.4272
River Rch & RM=PedlerRn,Main            ,12322
1006.704
River Rch & RM=PedlerRn,Main            ,11758.8
1027.066
River Rch & RM=PedlerRn,Main            ,8645.7
1171.865
River Rch & RM=PedlerRn,Main            ,6604.1
1241.308
River Rch & RM=PedlerRn,Main            ,6263.8
 1464.71
River Rch & RM=PedlerRn,Main            ,2015.4
1547.735
River Rch & RM=PedlerRn,Main            ,378.5
1717.186
River Rch & RM=PedlerRn,Main            ,30.3
1721.926
Boundary for River Rch & Prof#=PedlerRn,Main            , 1
Up Type= 0
Dn Type= 3
Dn Slope=0.005439
DSS Import GetInterval= 0
DSS Import GetPeak= 0
DSS Import FillOption= 0

--- PedlerRn.g01 (geometry) ---

Geom Title=USGS 3m DEM
Program Version=4.00

River Reach=PedlerRn     ,Main
Reach XY= 30
     1769419.478      292238.795     1769390.669      291698.216
     1769495.581      291139.227     1769123.942      290899.973
     1768758.947      290495.352     1768464.135      289666.649
     1767720.124      288962.855     1766763.462      287781.099
     1766700.300      287517.964     1766842.363      286787.873
     1766769.357      286457.126     1766569.934      286158.776
     1766383.061      286269.838     1766171.735      286174.875
     1765757.714      286188.051     1765057.966      285948.802
     1764600.038      285962.920     1764474.394      286063.869
     1764163.115      285759.279     1763744.937      286028.886
     1763687.516      285878.984     1763523.607      285911.271
     1763354.462      285623.400     1763245.329      285832.314
     1762840.703      285829.574     1762781.242      285395.975
     1762856.488      284974.490     1762631.689      284686.667
     1762487.527      284690.572     1762359.077      284526.336

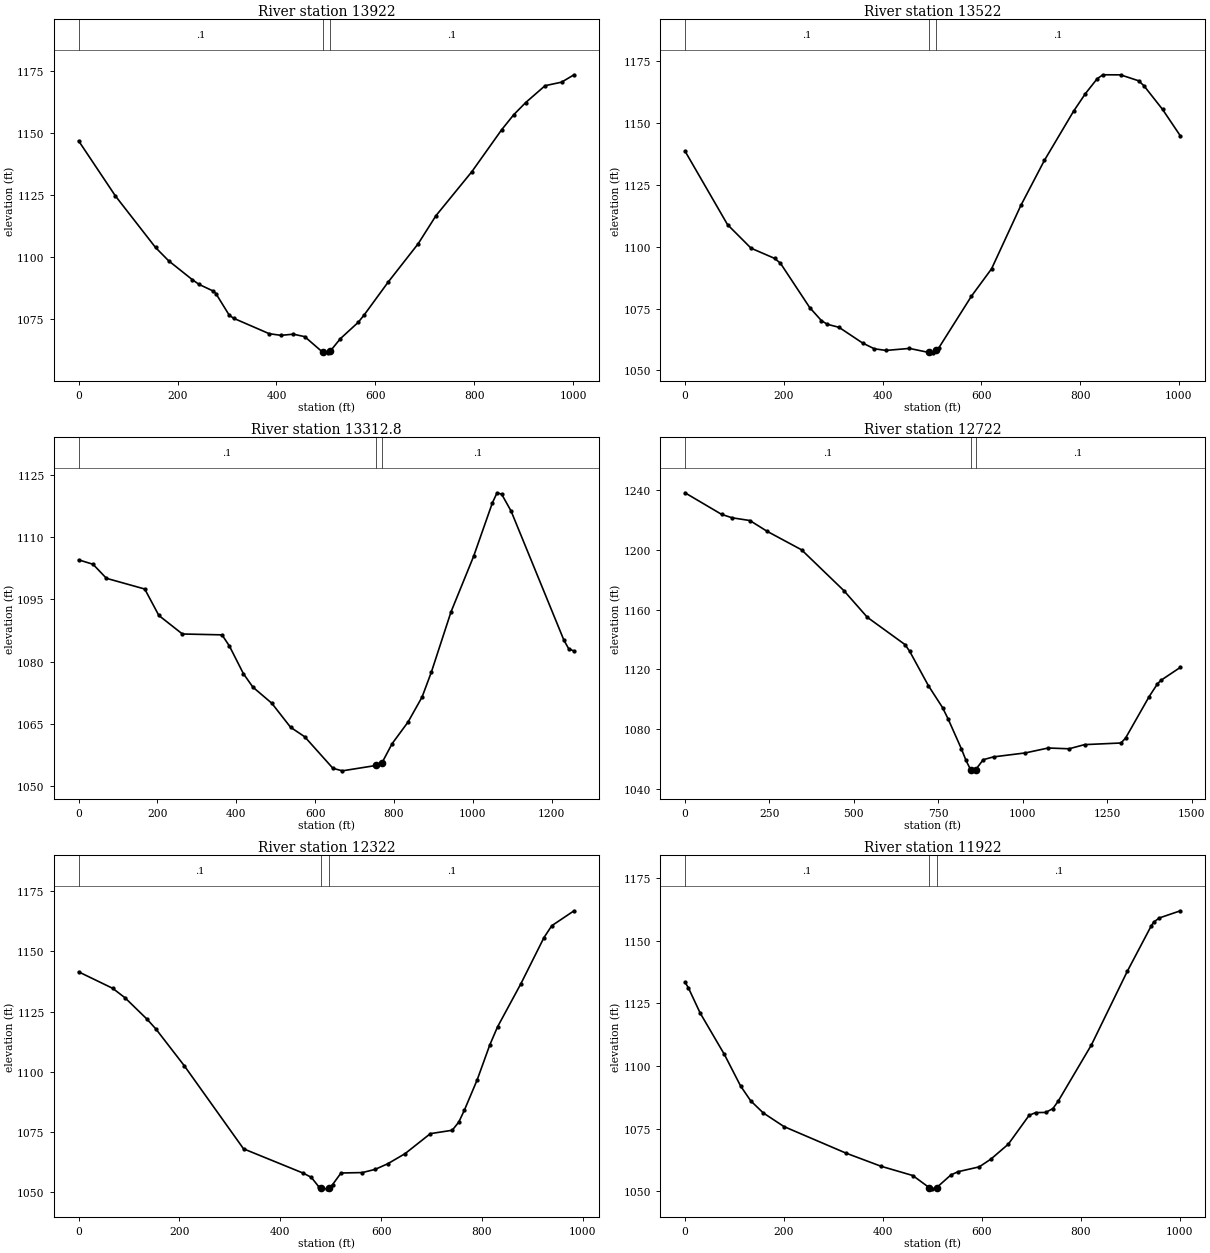
Type RM Length L Ch R = 1 ,13922,396.428,400,403.887
XS GIS Cut Line= 3
     1769915.416      292167.930     1769417.713      292228.952
     1768926.218      292322.789
#Sta/Elev= 30
       0 1146.82    74.4 1124.60   155.5 1103.82   182.1 1098.44   229.9 1090.85
   243.4 1088.95   272.7 1086.21   277.8 1085.17   304.6 1076.51   313.6 1075.26
   385.4 1069.06   409.3 1068.39   434.2 1068.87   457.2 1067.86   493.9 1061.52
   505.1 1061.34   508.9 1062.06   529.2 1067.04   565.5 1073.67   577.6 1076.68
   625.9 1089.87   686.4 1105.28   722.6 1116.66   795.2 1134.41   855.6 1151.36
   879.8 1157.36   903.9 1162.25   943.2 1169.07   976.5 1170.49  1001.8 1173.47
#Mann= 3 , 0 , 0
       0     0.1       0   493.9   0.045       0   508.9     0.1       0
Bank Sta=   493.9,   508.9
Exp/Cntr=0.3,0.1

Type RM Length L Ch R = 1 ,13522,212.198,209.248,207.483
XS GIS Cut Line= 3
     1769904.001      291850.547     1769403.051      291833.405
     1768901.253      291842.452
#Sta/Elev= 30
       0 1138.69    86.2 1108.92   133.8 1099.40   181.3 1095.30   193.2 1093.35
   252.6 1075.38   276.3 1070.11   288.2 1068.64   312.0 1067.40   359.5 1061.08
   383.2 1058.74   407.0 1058.06   454.5 1058.88   493.7 1057.24   501.2 1057.09
   508.7 1058.16   513.9 1059.09   580.1 1080.03   620.8 1091.08   680.1 1116.70
   727.6 1134.86   787.0 1154.85   810.8 1161.91   834.5 1167.90   846.1 1169.52
   882.0 1169.49   918.7 1167.08   929.5 1165.03   967.0 1155.51  1003.1 1144.79
#Mann= 3 , 0 , 0
       0     0.1       0   493.7   0.045       0   508.7     0.1       0
Bank Sta=   493.7,   508.7
Exp/Cntr=0.3,0.1

Type RM Length L Ch R = 1 ,13312.8,601.015,590.752,581.754
XS GIS Cut Line= 3
     1770174.704      291702.562     1769446.593      291630.654
     1768922.142      291654.290
#Sta/Elev= 30
       0 1104.54    36.5 1103.47    70.5 1100.09   167.7 1097.51   203.5 1091.14
   263.2 1086.68   363.7 1086.47   382.5 1083.77   418.0 1077.11   442.1 1073.87
   489.9 1070.01   537.6 1064.21   573.4 1061.93   645.0 1054.33   668.8 1053.72
   754.1 1055.01   769.1 1055.60   795.2 1060.27   835.4 1065.46   871.1 1071.49
   894.8 1077.53   944.6 1092.03  1001.8 1105.37  1049.4 1118.25  1061.3 1120.69
  1073.1 1120.33  1096.9 1116.28  1230.8 1085.20  1243.3 1083.07  1256.6 1082.59
#Mann= 3 , 0 , 0
       0     0.1       0   754.1   0.045       0   769.1     0.1       0
Bank Sta=   754.1,   769.1
Exp/Cntr=0.3,0.1

Type RM Length L Ch R = 1 ,12722,404.868,400,395.581
XS GIS Cut Line= 3
     1770183.687      290636.521     1769455.663      291080.863
     1768914.941      291371.451
#Sta/Elev= 30
       0 1238.32   108.7 1223.81   139.7 1221.54   192.2 1219.71   243.3 1212.47
   345.2 1200.07   470.4 1172.72   539.9 1154.83   651.2 1136.57   665.1 1132.09
   720.7 1108.98   762.5 1094.30   778.9 1086.75   818.1 1066.77   832.0 1058.90
   845.4 1052.72   848.0 1051.86   860.4 1052.58   883.0 1059.33   913.5 1061.22
  1007.9 1063.89  1075.3 1067.17  1137.2 1066.65  1183.1 1069.44  1290.9 1070.53
  1304.4 1073.80  1373.9 1101.51  1398.8 1110.17  1409.0 1112.53  1466.8 1121.27
#Mann= 3 , 0 , 0
       0     0.1       0   845.4   0.045       0   860.4     0.1       0
Bank Sta=   845.4,   860.4
Exp/Cntr=0.3,0.1

Type RM Length L Ch R = 1 ,12322,401.101,400,396.96
XS GIS Cut Line= 3
     1769473.844      290558.493     1769120.896      290895.992
     1768738.818      291209.556
#Sta/Elev= 30
       0 1141.53    67.5 1134.70    92.0 1130.77   136.2 1121.78   153.4 1117.78
   209.6 1102.56   327.1 1068.09   445.4 1058.01   461.5 1056.26   476.9 1052.21
   480.8 1051.74   493.0 1051.49   495.8 1051.88   503.6 1053.23   520.4 1058.06
   562.6 1058.24   587.9 1059.55   613.2 1061.91   647.5 1066.10   697.6 1074.39
   741.0 1075.80   754.1 1079.23   765.1 1084.15   790.4 1096.68   815.5 1111.22
   830.9 1118.73   876.9 1136.50   923.0 1155.77   938.4 1160.67   982.6 1166.87
#Mann= 3 , 0 , 0
       0     0.1       0   480.8   0.045       0   495.8     0.1       0
Bank Sta=   480.8,   495.8
Exp/Cntr=0.3,0.1

Type RM Length L Ch R = 1 ,11922,155.084,163.186,172.05
XS GIS Cut Line= 3
     1769211.728      290226.705     1768866.977      290590.386
     1768526.358      290956.951
#Sta/Elev= 30
       0 1133.45     6.9 1131.18    30.7 1121.11    79.7 1104.57   112.5 1091.97
   132.9 1086.06   158.1 1081.26   200.1 1075.79   325.1 1065.22   396.1 1059.96
   460.4 1056.25   493.6 1051.44   499.6 1050.93   508.6 1051.40   537.5 1056.46
   551.9 1057.76   594.8 1059.70   618.5 1062.81   653.6 1068.76   695.7 1080.27
   708.9 1081.37   729.3 1081.43   743.8 1082.99   754.5 1085.94   821.7 1108.41
   894.0 1137.71   942.6 1155.92   947.7 1157.43   958.8 1159.06  1001.5 1161.93
#Mann= 3 , 0 , 0
       0     0.1       0   493.6   0.045       0   508.6     0.1       0
Bank Sta=   493.6,   508.6
Exp/Cntr=0.3,0.1

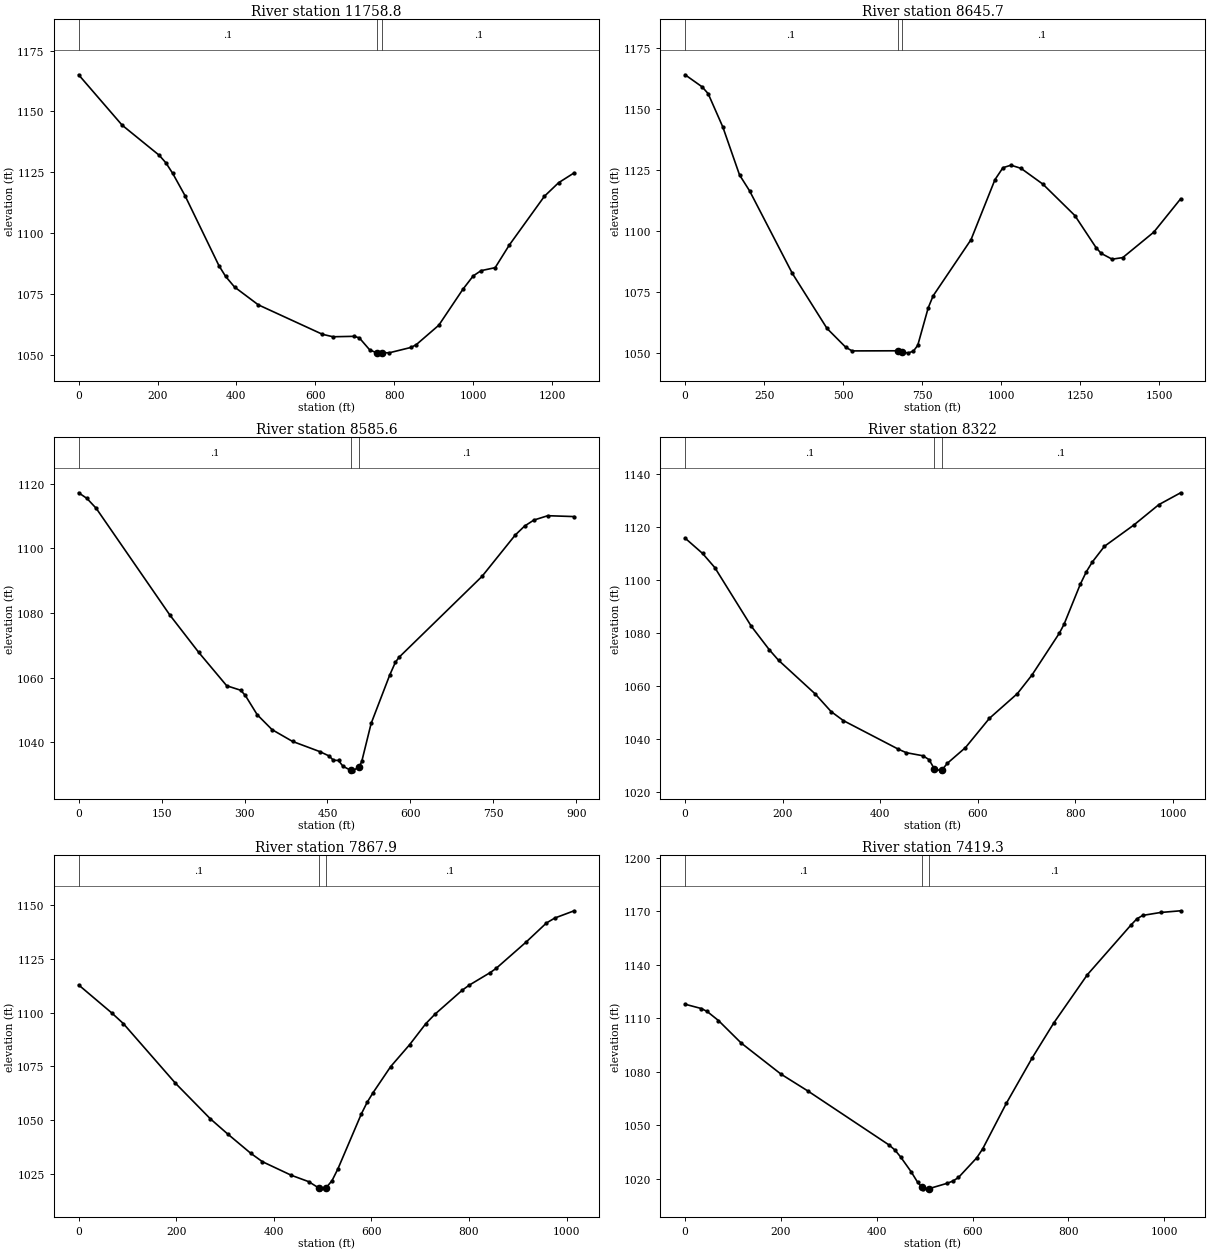
Type RM Length L Ch R = 1 ,11758.8,3118.668,3113.135,3107.065
XS GIS Cut Line= 4
     1769357.206      290022.649     1768941.563      290381.244
     1768757.140      290475.255     1768303.714      290687.013
#Sta/Elev= 30
       0 1165.02   110.2 1144.32   204.3 1131.93   221.1 1128.85   238.4 1124.51
   269.8 1115.30   355.8 1086.52   372.6 1082.14   395.2 1077.77   455.5 1070.44
   618.2 1058.32   644.9 1057.31   698.2 1057.49   711.5 1056.88   738.1 1051.90
   755.4 1050.72   764.6 1050.70   770.4 1050.70   788.1 1050.74   843.3 1052.95
   856.4 1054.11   913.2 1062.06   974.3 1076.84  1000.5 1082.34  1020.4 1084.49
  1056.1 1085.72  1091.8 1094.99  1181.1 1115.10  1216.9 1120.64  1256.4 1124.70
#Mann= 3 , 0 , 0
       0     0.1       0   755.4   0.045       0   770.4     0.1       0
Bank Sta=   755.4,   770.4
Exp/Cntr=0.3,0.1

Type RM Length L Ch R = 1 ,8645.7,59.864,60.054,59.584
XS GIS Cut Line= 3
     1767470.672      287615.072     1766961.155      288024.104
     1766266.884      288618.229
#Sta/Elev= 30
       0 1163.95    54.0 1159.00    72.9 1156.23   119.5 1142.53   172.2 1122.96
   204.0 1116.46   339.1 1082.72   448.9 1060.18   508.0 1052.50   528.1 1051.00
   671.8 1051.05   686.8 1050.37   706.4 1050.21   722.0 1050.90   735.8 1053.29
   768.9 1068.63   784.5 1073.54   904.2 1096.49   980.0 1121.06  1005.2 1125.93
  1030.5 1126.97  1062.3 1125.68  1131.5 1119.22  1232.6 1106.38  1299.7 1093.25
  1315.8 1090.90  1350.5 1088.52  1384.2 1089.17  1482.3 1099.58  1567.2 1113.21
#Mann= 3 , 0 , 0
       0     0.1       0   671.8   0.045       0   686.8     0.1       0
Bank Sta=   671.8,   686.8
Exp/Cntr=0.3,0.1

Type RM Length L Ch R = 1 ,8585.6,255.289,263.625,273.566
XS GIS Cut Line= 3
     1767286.891      287673.187     1766903.835      287994.873
     1766608.325      288258.445
#Sta/Elev= 30
       0 1117.14    15.0 1115.40    31.8 1112.33   165.2 1079.28   217.2 1067.79
   267.8 1057.47   293.1 1056.08   301.5 1054.46   322.9 1048.53   349.8 1043.90
   386.8 1040.26   436.3 1037.10   453.2 1035.74   460.6 1034.44   470.0 1034.37
   478.0 1032.58   492.2 1031.31   495.3 1031.16   507.2 1032.34   512.1 1034.11
   529.0 1045.81   562.6 1060.77   572.8 1064.70   579.4 1066.26   729.5 1091.28
   789.6 1104.07   806.5 1106.84   823.3 1108.70   848.5 1110.05   896.2 1109.78
#Mann= 3 , 0 , 0
       0     0.1       0   492.2   0.045       0   507.2     0.1       0
Bank Sta=   492.2,   507.2
Exp/Cntr=0.3,0.1

Type RM Length L Ch R = 1 ,8322,446.535,454.14,464.109
XS GIS Cut Line= 3
     1767251.577      287605.680     1766761.241      287773.601
     1766284.364      287914.862
#Sta/Elev= 30
       0 1115.69    35.8 1109.93    60.9 1104.60   135.4 1082.59   172.8 1073.61
   191.5 1069.70   266.3 1057.09   299.3 1050.37   324.4 1046.98   437.4 1036.19
   453.3 1034.90   487.6 1033.73   500.1 1032.26   510.8 1028.82   525.1 1028.06
   525.8 1028.22   537.5 1030.90   574.7 1036.82   623.8 1047.84   681.1 1057.15
   710.9 1064.12   767.1 1079.90   776.7 1083.24   809.9 1098.27   822.3 1102.99
   834.7 1106.71   859.5 1112.61   920.0 1120.66   970.9 1128.29  1015.7 1132.77
#Mann= 3 , 0 , 0
       0     0.1       0   510.8   0.045       0   525.8     0.1       0
Bank Sta=   510.8,   525.8
Exp/Cntr=0.3,0.1

Type RM Length L Ch R = 1 ,7867.9,450.061,448.529,438.522
XS GIS Cut Line= 3
     1767238.090      287343.113     1766741.097      287347.205
     1766228.804      287266.701
#Sta/Elev= 30
       0 1112.82    67.9 1099.80    91.6 1094.87   198.5 1067.13   269.7 1050.67
   305.3 1043.60   352.8 1034.59   376.6 1030.70   435.9 1024.38   471.6 1021.41
     492 1018.50   495.3 1018.08     507 1018.54   519.3 1021.87   531.3 1027.31
   579.4 1052.88   591.4 1058.32   603.5 1062.78   639.5 1074.87   678.3 1085.04
   711.6 1094.84   730.2 1099.20   785.9 1110.32   800.2 1112.67   843.8 1118.59
   855.8 1120.53   917.1 1132.73   958.7 1141.59   976.0 1143.91  1015.6 1147.27
#Mann= 3 , 0 , 0
       0     0.1       0     492   0.045       0     507     0.1       0
Bank Sta=     492,     507
Exp/Cntr=0.3,0.1

Type RM Length L Ch R = 1 ,7419.3,302.83,297.331,295.339
XS GIS Cut Line= 3
     1767323.030      286928.678     1766827.142      286926.416
     1766310.666      287078.608
#Sta/Elev= 30
       0 1117.89    34.1 1115.46    46.0 1113.82    69.7 1108.72   117.2 1096.06
   200.3 1078.60   256.8 1069.07   425.9 1038.80   437.8 1036.04   449.6 1032.20
   471.5 1023.92   485.3 1017.91   493.6 1015.34   497.2 1014.35   505.0 1014.20
   508.6 1014.27   546.7 1017.29   559.1 1018.59   570.6 1020.58   608.6 1031.58
   621.0 1036.60   670.5 1062.24   724.9 1087.94   769.5 1107.37   839.6 1134.47
   930.4 1162.31   942.8 1165.81   955.1 1167.78   992.3 1169.42  1034.3 1170.38
#Mann= 3 , 0 , 0
       0     0.1       0   493.6   0.045       0   508.6     0.1       0
Bank Sta=   493.6,   508.6
Exp/Cntr=0.3,0.1

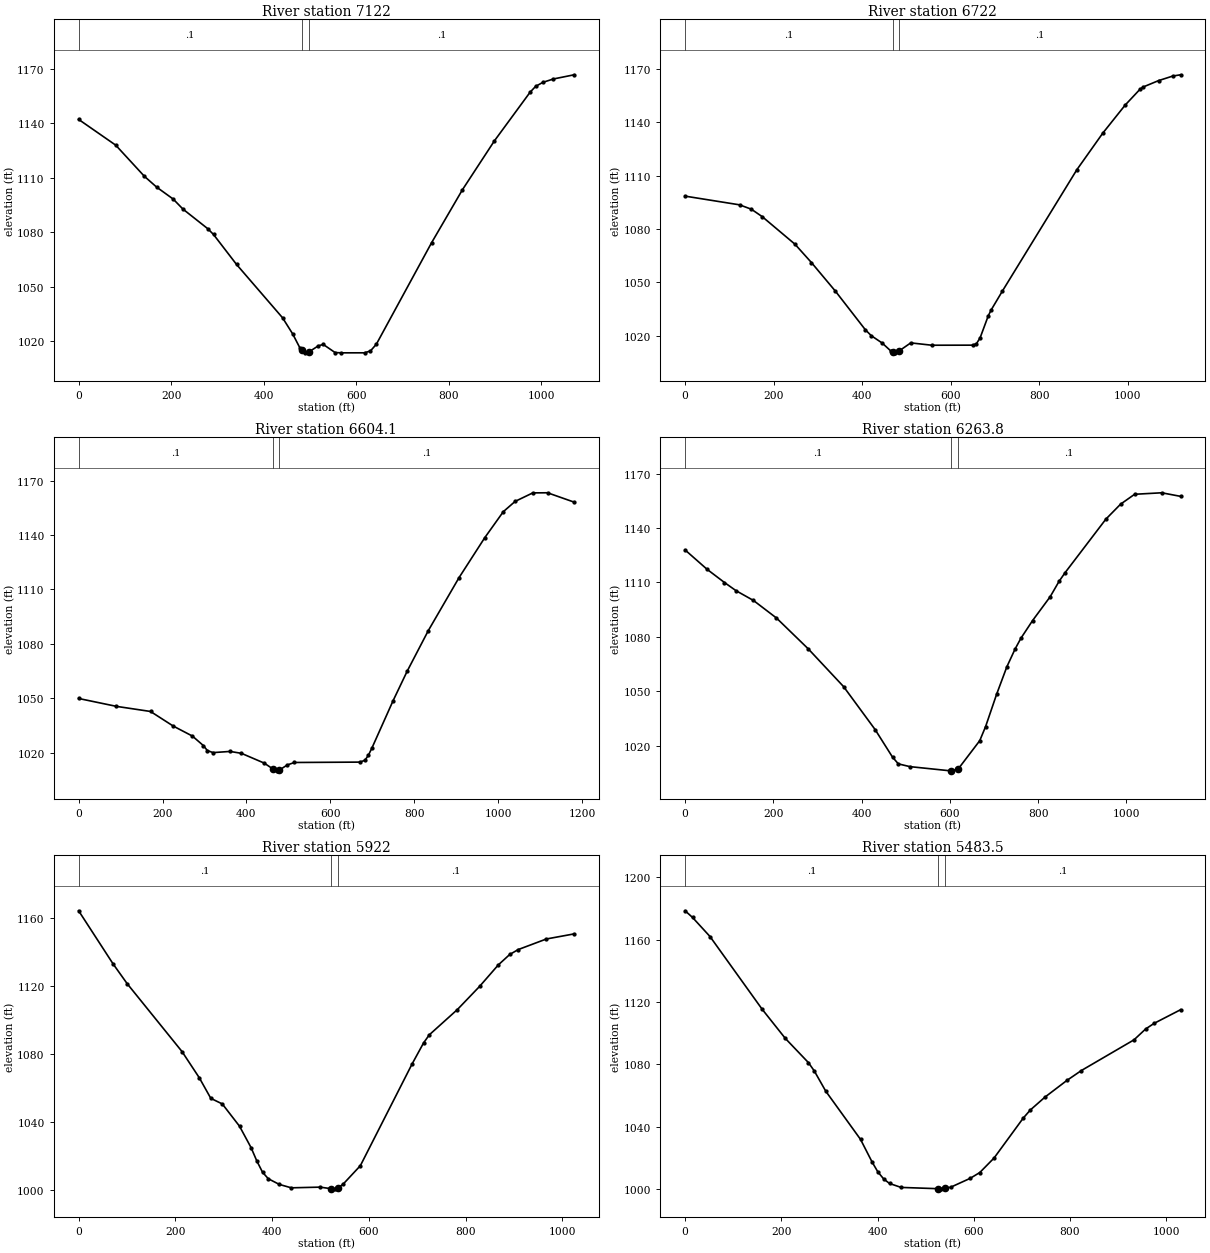
Type RM Length L Ch R = 1 ,7122,404.505,400,389.568
XS GIS Cut Line= 3
     1767270.462      286492.806     1766802.380      286638.983
     1766261.766      286851.835
#Sta/Elev= 30
       0 1142.16    80.2 1127.99   142.3 1110.82   168.8 1104.87   204.5 1098.31
   225.7 1092.77   279.2 1082.01   291.6 1078.84   341.4 1062.34   440.9 1032.98
   462.7 1024.15   478.2 1016.50   482.9 1015.04   490.4 1013.78   497.9 1014.21
   518.5 1017.58   528.9 1018.31   554.4 1013.86   567.2 1013.69   618.2 1013.70
   631.0 1014.75   643.7 1018.44   763.1 1074.29   829.8 1103.45   898.9 1130.35
   976.3 1157.20   988.2 1160.38  1003.8 1162.57  1026.5 1164.42  1071.4 1166.73
#Mann= 3 , 0 , 0
       0     0.1       0   482.9   0.045       0   497.9     0.1       0
Bank Sta=   482.9,   497.9
Exp/Cntr=0.3,0.1

Type RM Length L Ch R = 1 ,6722,117.872,117.858,119.639
XS GIS Cut Line= 3
     1767064.249      286057.087     1766646.850      286286.543
     1766210.774      286759.543
#Sta/Elev= 30
       0 1098.54   123.0 1093.65   149.6 1091.20   174.2 1087.02   248.2 1071.52
   285.5 1061.18   339.7 1045.08   407.5 1023.33   421.0 1020.00   445.3 1015.94
   464.6 1011.52   468.8 1011.04   475.2 1010.42   483.8 1011.53   509.9 1016.02
   557.5 1014.70   649.8 1014.74   658.3 1015.55   666.7 1018.92   685.1 1031.29
   691.9 1034.68   717.1 1045.22   885.2 1113.39   944.0 1134.03   994.4 1149.75
  1028.0 1158.67  1035.4 1159.95  1069.7 1163.49  1102.0 1166.07  1119.7 1166.78
#Mann= 3 , 0 , 0
       0     0.1       0   468.8   0.045       0   483.8     0.1       0
Bank Sta=   468.8,   483.8
Exp/Cntr=0.3,0.1

Type RM Length L Ch R = 1 ,6604.1,354.953,340.389,332.116
XS GIS Cut Line= 3
     1766999.821      285958.549     1766582.421      286188.005
     1766106.263      286707.956
#Sta/Elev= 30
       0 1049.82    90.1 1045.47   171.4 1042.65   225.6 1034.59   271.2 1029.08
   297.4 1023.82   306.9 1021.08   320.4 1019.95   361.0 1020.60   388.1 1019.55
   442.3 1014.17   463.8 1010.83   472.2 1009.89   478.8 1010.39   497.6 1013.15
   514.4 1014.50   670.2 1014.71   682.5 1015.71   690.9 1018.55   699.3 1022.55
   749.7 1048.63   783.3 1064.92   833.7 1087.32   906.9 1116.53   968.2 1138.56
  1012.4 1152.90  1040.5 1158.57  1082.7 1163.27  1117.8 1163.33  1181.3 1158.16
#Mann= 3 , 0 , 0
       0     0.1       0   463.8   0.045       0   478.8     0.1       0
Bank Sta=   463.8,   478.8
Exp/Cntr=0.3,0.1

Type RM Length L Ch R = 1 ,6263.8,353.285,341.753,329.756
XS GIS Cut Line= 3
     1766594.206      285692.238     1766333.442      286243.935
     1766102.094      286701.673
#Sta/Elev= 30
       0 1127.94    49.9 1117.26    89.3 1109.98   115.6 1105.46   155.0 1100.08
   207.1 1090.41   279.0 1073.43   359.2 1052.58   430.7 1028.88   470.1 1013.69
   483.3 1009.97   509.5 1008.45   601.4 1006.13   603.3 1006.21   618.3 1006.95
   667.8 1022.77   681.1 1030.57   706.1 1048.41   729.2 1063.49   747.7 1073.22
   761.0 1079.22   787.6 1089.03   827.5 1102.18   847.5 1110.61   860.8 1115.29
   953.6 1144.93   987.1 1153.22  1018.8 1158.65  1080.2 1159.48  1123.1 1157.50
#Mann= 3 , 0 , 0
       0     0.1       0   603.3   0.045       0   618.3     0.1       0
Bank Sta=   603.3,   618.3
Exp/Cntr=0.3,0.1

Type RM Length L Ch R = 1 ,5922,432.388,438.545,442.041
XS GIS Cut Line= 3
     1765996.081      285690.094     1766023.550      286218.640
     1766039.747      286713.405
#Sta/Elev= 30
       0 1164.11    71.1 1132.92   100.3 1121.25   213.8 1081.27   249.4 1065.90
   273.2 1053.80   297.0 1050.49   332.6 1037.39   356.4 1024.83   368.3 1016.98
   380.2 1010.31   392.1 1006.50   414.9 1003.16   439.6 1001.17   499.1 1001.57
   521.8 1000.66   529.3 1000.57   536.8 1001.21   546.6 1003.29   582.3 1014.17
   689.2 1073.98   712.9 1086.34   724.8 1091.14   782.8 1105.99   828.8 1119.64
   867.4 1132.24   891.1 1138.41   908.5 1141.28   966.8 1147.52  1024.3 1150.52
#Mann= 3 , 0 , 0
       0     0.1       0   521.8   0.045       0   536.8     0.1       0
Bank Sta=   521.8,   536.8
Exp/Cntr=0.3,0.1

Type RM Length L Ch R = 1 ,5483.5,397.402,408.061,415.517
XS GIS Cut Line= 3
     1765736.130      285638.828     1765648.442      286167.698
     1765549.953      286652.005
#Sta/Elev= 30
       0 1178.54    15.4 1174.28    51.7 1162.04   159.9 1115.48   208.2 1096.71
   256.3 1081.15   268.4 1075.85   292.4 1062.79   364.6 1031.90   388.7 1017.35
   400.7 1011.01   412.8 1006.51   424.8 1003.64   448.9 1001.11   524.9 1000.30
   531.7 1000.20   539.9 1000.46   552.0 1001.25   592.3 1006.91   612.4 1010.66
   642.1 1019.98   702.7 1045.57   717.5 1050.79   747.9 1059.04   793.6 1069.77
   823.6 1076.09   932.9 1095.77   957.1 1102.74   974.9 1106.37  1029.8 1115.10
#Mann= 3 , 0 , 0
       0     0.1       0   524.9   0.045       0   539.9     0.1       0
Bank Sta=   524.9,   539.9
Exp/Cntr=0.3,0.1

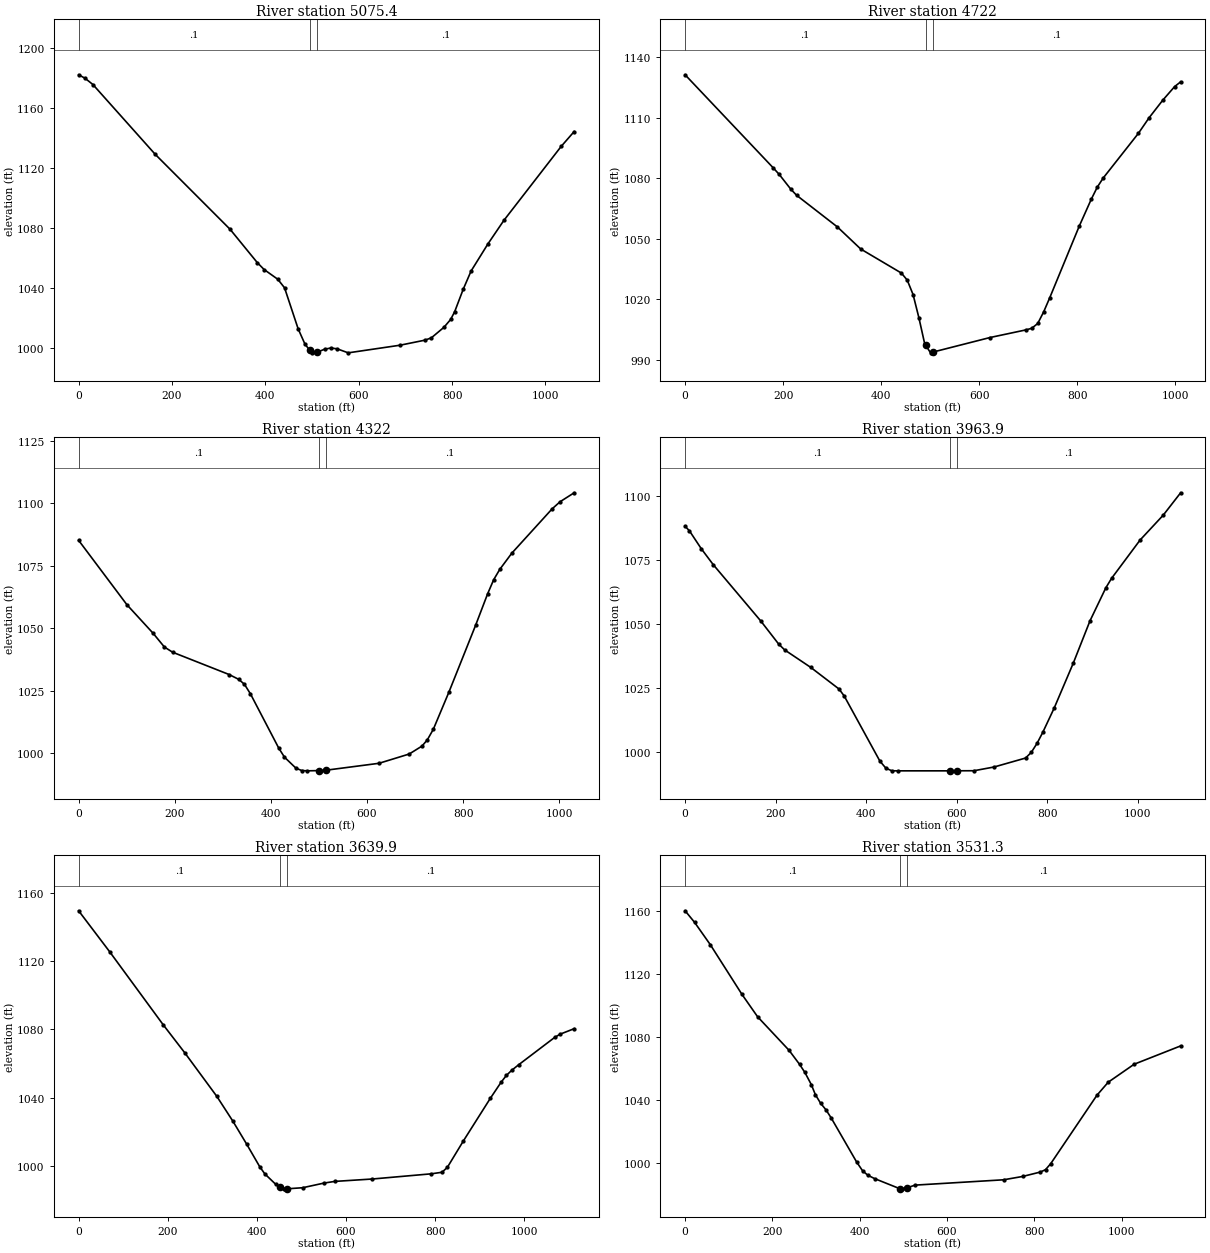
Type RM Length L Ch R = 1 ,5075.4,367.213,353.394,346.317
XS GIS Cut Line= 3
     1765654.444      285579.939     1765361.413      285991.319
     1765099.139      286482.051
#Sta/Elev= 30
       0 1182.23    13.5 1179.95    30.6 1175.72   164.1 1129.13   324.5 1079.09
   382.8 1056.84   397.3 1052.27   426.5 1045.80   441.1 1040.07   470.2 1012.71
   484.8 1002.50   495.1  998.40   499.4  996.76   510.1  996.96   526.7  999.08
   540.2  999.90   553.7  999.35   577.5  996.67   688.3 1001.75   742.1 1005.15
   755.6 1006.69   782.5 1013.70   796.9 1018.95   805.6 1024.18   823.7 1039.01
   840.7 1051.28   876.7 1069.34   910.9 1085.05  1033.7 1134.44  1061.5 1144.36
#Mann= 3 , 0 , 0
       0     0.1       0   495.1   0.045       0   510.1     0.1       0
Bank Sta=   495.1,   510.1
Exp/Cntr=0.3,0.1

Type RM Length L Ch R = 1 ,4722,398.903,400,387.6
XS GIS Cut Line= 3
     1765054.555      285450.417     1765041.948      285948.397
     1764932.755      286450.537
#Sta/Elev= 30
       0 1131.23   180.1 1085.07   192.0 1081.91   215.8 1074.56   227.6 1071.55
   310.8 1055.89   358.3 1044.98   441.4 1033.05   453.3 1029.56   465.2 1022.42
   477.0 1011.02   488.9  998.06   490.6  997.41   500.9  993.56   505.6  993.93
   622.4 1001.15   695.3 1004.91   707.3 1005.71   719.6 1008.09   731.7 1013.85
   743.9 1020.72   804.6 1056.46   828.9 1069.64   841.1 1075.59   853.2 1080.12
   924.8 1102.17   946.9 1109.97   974.7 1118.64   999.0 1125.40  1011.2 1127.72
#Mann= 3 , 0 , 0
       0     0.1       0   490.6   0.045       0   505.6     0.1       0
Bank Sta=   490.6,   505.6
Exp/Cntr=0.3,0.1

Type RM Length L Ch R = 1 ,4322,352.605,358.061,371.258
XS GIS Cut Line= 3
     1764678.751      285452.431     1764643.288      285958.418
     1764814.478      286453.607
#Sta/Elev= 30
       0 1085.20   100.4 1059.45   154.7 1048.07   178.5 1042.50   195.5 1040.43
   313.1 1031.50   333.2 1029.56   345.1 1027.58   357.6 1023.74   416.5 1002.02
   428.4  998.41   452.2  994.02   464.1  993.08   476.0  992.95   499.7  993.05
   514.7  993.20   625.1  995.97   687.9  999.68   714.6 1002.87   725.6 1005.35
   738.1 1009.58   770.6 1024.48   826.1 1051.21   851.2 1063.85   863.7 1069.44
   876.3 1073.56   901.4 1080.06   985.3 1097.80  1001.9 1100.66  1031.2 1104.24
#Mann= 3 , 0 , 0
       0     0.1       0   499.7   0.045       0   514.7     0.1       0
Bank Sta=   499.7,   514.7
Exp/Cntr=0.3,0.1

Type RM Length L Ch R = 1 ,3963.9,328.822,324.043,319.264
XS GIS Cut Line= 3
     1764635.063      285443.801     1764390.058      285957.265
     1764206.199      286450.307
#Sta/Elev= 30
       0 1088.20     9.5 1086.44    35.8 1079.43    62.2 1073.22   167.4 1051.22
   206.6 1042.29   220.0 1039.97   277.8 1033.13   340.2 1024.71   351.6 1022.00
   430.5  996.59   443.7  993.84   456.8  992.82   470.0  992.80   586.5  992.80
   601.5  992.82   638.3  992.84   682.9  994.30   752.4  997.79   765.0  999.99
   777.7 1003.50   790.4 1007.80   815.7 1017.31   857.9 1034.83   894.8 1051.32
   929.8 1064.19   942.4 1067.87  1005.6 1082.85  1056.5 1092.50  1095.1 1101.26
#Mann= 3 , 0 , 0
       0     0.1       0   586.5   0.045       0   601.5     0.1       0
Bank Sta=   586.5,   601.5
Exp/Cntr=0.3,0.1

Type RM Length L Ch R = 1 ,3639.9,107.79,108.606,108.365
XS GIS Cut Line= 3
     1764257.388      285312.373     1764199.393      285672.064
     1764078.184      286409.881
#Sta/Elev= 30
       0 1149.37    69.7 1125.38   189.9 1082.64   238.1 1066.32   310.2 1040.77
   346.3 1026.22   377.5 1012.67   406.4  999.64   417.9  995.43   442.5  989.30
   452.3  987.51   460.2  986.73   466.6  986.71   467.3  986.72   502.7  987.36
   550.8  990.09   574.9  991.06   659.1  992.46   791.5  995.50   815.5  996.41
   827.5  999.31   863.6 1014.83   923.8 1039.64   947.9 1049.02   959.9 1053.07
   971.9 1056.06   987.2 1059.25  1068.2 1075.28  1080.2 1077.15  1112.0 1080.40
#Mann= 3 , 0 , 0
       0     0.1       0   452.3   0.045       0   467.3     0.1       0
Bank Sta=   452.3,   467.3
Exp/Cntr=0.3,0.1

Type RM Length L Ch R = 1 ,3531.3,409.705,409.29,396.205
XS GIS Cut Line= 3
     1764167.954      285300.279     1764088.706      285789.758
     1764010.553      286424.398
#Sta/Elev= 30
       0 1160.24    21.8 1152.87    57.9 1138.67   130.1 1107.26   166.1 1092.98
   238.3 1071.65   262.4 1062.71   274.4 1057.66   289.2 1049.91   298.4 1043.58
   310.5 1038.07   322.5 1034.01   334.5 1028.87   392.7 1000.94   406.7  995.19
   418.7  992.40   434.2  990.26   492.3  983.82   495.9  983.77   507.3  984.30
   526.8  986.13   729.6  989.51   773.2  991.62   813.9  994.43   825.8  995.96
   837.8  999.80   943.6 1043.19   969.4 1051.45  1028.8 1062.85  1135.3 1074.48
#Mann= 3 , 0 , 0
       0     0.1       0   492.3   0.045       0   507.3     0.1       0
Bank Sta=   492.3,   507.3
Exp/Cntr=0.3,0.1

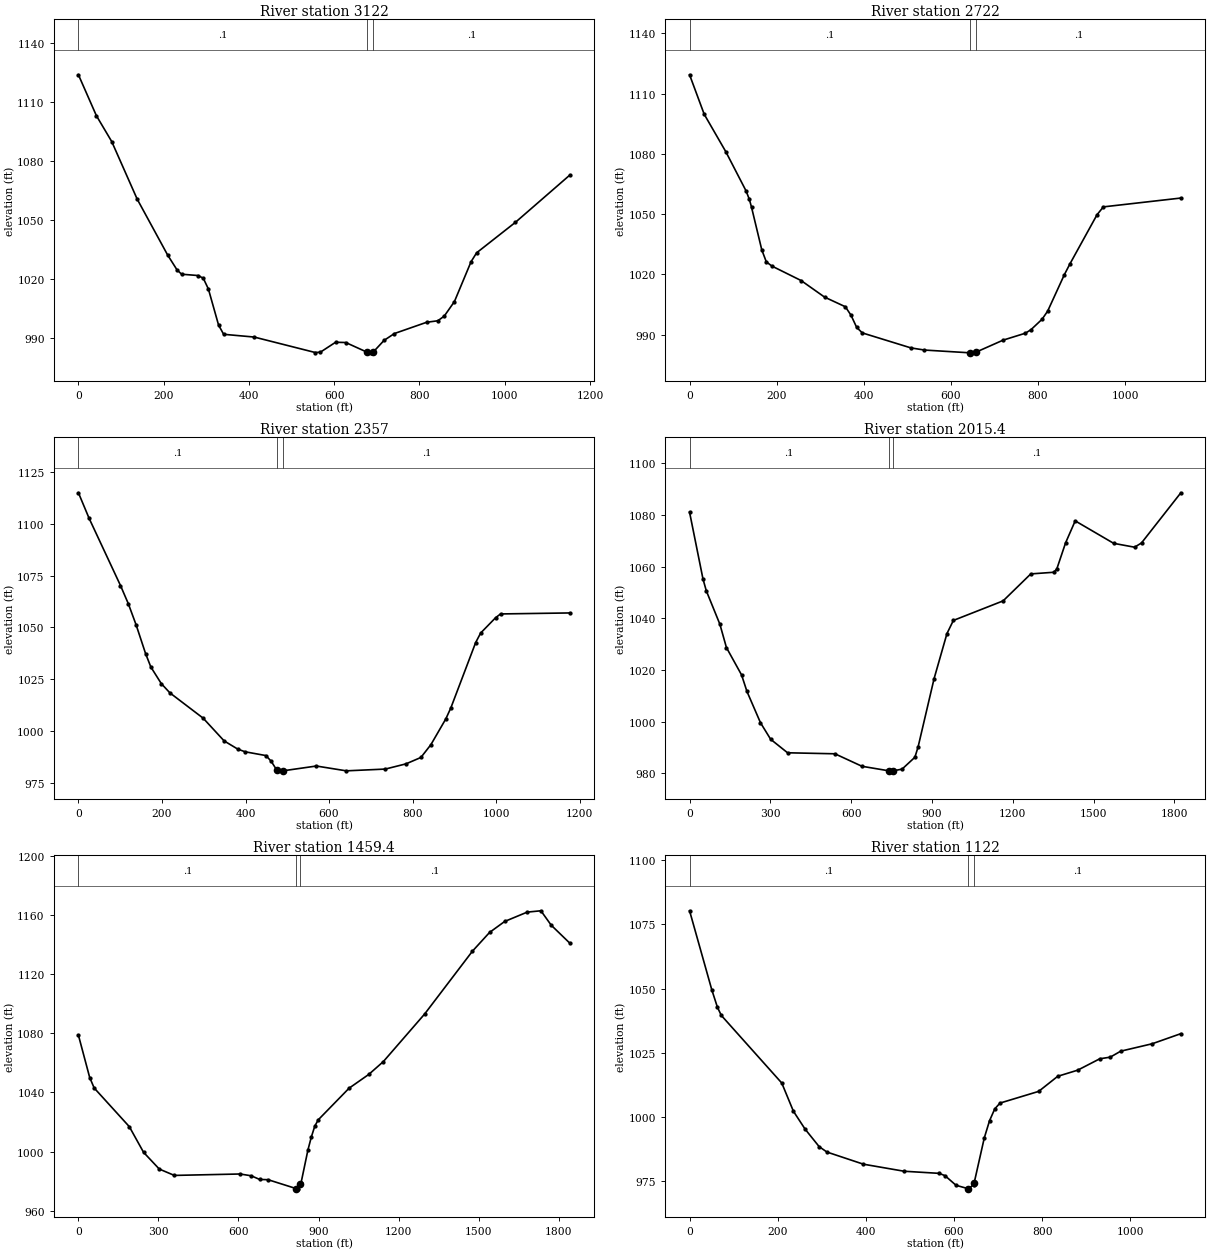
Type RM Length L Ch R = 1 ,3122,395.044,400,418.178
XS GIS Cut Line= 3
     1763855.852      285339.105     1763785.086      286019.845
     1763975.681      286447.327
#Sta/Elev= 30
       0 1123.83    42.3 1102.94    78.1 1089.84   137.8 1060.53   209.4 1032.00
   231.2 1024.52   242.0 1022.27   281.0 1021.59   293.0 1020.19   304.9 1014.74
   328.8  996.36   340.7  991.67   412.3  990.27   555.5  982.40   567.5  982.55
   603.3  987.62   627.2  987.48   676.9  982.58   687.1  982.23   691.9  982.70
   717.0  988.57   741.3  992.06   817.1  997.81   843.1  998.56   858.2 1000.93
   882.1 1008.35   921.1 1028.63   934.1 1033.16  1025.1 1048.68  1152.5 1072.70
#Mann= 3 , 0 , 0
       0     0.1       0   676.9   0.045       0   691.9     0.1       0
Bank Sta=   676.9,   691.9
Exp/Cntr=0.3,0.1

Type RM Length L Ch R = 1 ,2722,368.58,365.008,349.569
XS GIS Cut Line= 3
     1763784.293      285314.817     1763523.004      285910.474
     1763345.191      286353.625
#Sta/Elev= 30
       0 1119.39    33.6 1099.73    83.2 1081.09   129.8 1061.52   137.3 1057.32
   142.3 1053.39   165.8 1032.21   176.2 1026.24   189.1 1024.14   256.0 1016.95
   310.0 1008.69   357.7 1003.89   370.6  999.69   383.6  993.63   396.6  990.87
   508.3  983.40   539.2  982.34   642.9  980.97   644.7  980.95   657.9  981.32
   719.8  987.27   770.9  990.72   783.7  992.46   809.3  997.68   822.1 1001.72
   860.5 1019.89   873.3 1025.26   935.5 1049.72   950.0 1053.62  1127.9 1058.02
#Mann= 3 , 0 , 0
       0     0.1       0   642.9   0.045       0   657.9     0.1       0
Bank Sta=   642.9,   657.9
Exp/Cntr=0.3,0.1

Type RM Length L Ch R = 1 ,2357,337.777,341.572,342.861
XS GIS Cut Line= 3
     1763524.372      285169.499     1763371.513      285620.596
     1763310.916      286317.816
#Sta/Elev= 30
       0 1114.88    25.7 1102.52   100.7 1070.20   119.4 1061.46   138.1 1051.25
   160.8 1037.39   173.4 1030.93   198.4 1022.93   219.1 1018.45   298.7 1006.26
   348.9  995.31   381.5  991.37   399.0  990.08   449.1  988.25   461.7  985.44
   474.6  981.34   489.6  980.91   569.7  983.22   641.2  980.90   734.6  981.75
   784.2  984.26   819.9  987.35   843.8  993.51   879.5 1005.92   891.6 1011.24
   951.0 1042.72   962.9 1047.29   998.7 1054.68  1010.6 1056.50  1176.1 1056.98
#Mann= 3 , 0 , 0
       0     0.1       0   474.6   0.045       0   489.6     0.1       0
Bank Sta=   474.6,   489.6
Exp/Cntr=0.3,0.1

Type RM Length L Ch R = 1 ,2015.4,549.656,555.975,582.422
XS GIS Cut Line= 3
     1763426.618      285144.131     1763181.244      285855.264
     1763102.921      286923.938
#Sta/Elev= 30
       0 1081.01    49.8 1055.17    62.1 1050.60   112.6 1037.64   136.8 1028.63
   192.9 1018.06   213.1 1011.62   263.3  999.51   301.0  993.12   363.8  987.89
   539.6  987.50   640.1  982.66   740.5  980.90   755.5  980.90   788.8  981.56
   836.4  986.15   848.3  990.13   907.8 1016.63   955.5 1034.04   979.3 1039.13
  1164.0 1046.70  1266.7 1057.14  1352.2 1057.78  1363.3 1059.06  1395.9 1069.17
  1431.6 1077.67  1574.5 1068.97  1652.1 1067.48  1677.8 1069.14  1823.8 1088.55
#Mann= 3 , 0 , 0
       0     0.1       0   740.5   0.045       0   755.5     0.1       0
Bank Sta=   740.5,   755.5
Exp/Cntr=0.3,0.1

Type RM Length L Ch R = 1 ,1459.4,330.282,337.445,348.303
XS GIS Cut Line= 3
     1763407.811      285120.946     1762786.749      285663.222
     1761846.562      286050.876
#Sta/Elev= 30
       0 1078.78    42.3 1050.10    59.1 1043.01   190.8 1016.85   244.2  999.47
   303.1  988.15   359.5  983.84   606.0  984.80   647.9  983.58   679.4  981.10
   710.9  980.94   817.2  974.86   821.2  974.75   832.2  978.09   834.7  978.94
   860.4 1001.15   873.2 1009.94   886.0 1017.19   898.9 1021.46  1014.5 1042.88
  1088.5 1052.23  1143.1 1060.92  1297.7 1093.10  1476.8 1135.62  1541.0 1148.31
  1597.7 1155.76  1682.3 1162.10  1733.6 1163.00  1772.2 1153.24  1841.5 1141.15
#Mann= 3 , 0 , 0
       0     0.1       0   817.2   0.045       0   832.2     0.1       0
Bank Sta=   817.2,   832.2
Exp/Cntr=0.3,0.1

Type RM Length L Ch R = 1 ,1122,402.341,400,389.681
XS GIS Cut Line= 3
     1763356.912      285045.002     1762783.821      285326.040
     1762308.963      285289.468
#Sta/Elev= 30
       0 1080.33    50.5 1049.52    63.3 1042.71    72.1 1039.57   209.2 1013.26
   235.6 1002.28   262.0  995.34   294.0  988.50   311.7  986.39   394.3  981.67
   486.8  978.92   566.2  978.10   579.4  977.21   604.5  973.46   630.8  972.18
   632.3  972.07   644.8  973.74   645.8  974.48   668.6  991.87   680.5  998.57
   692.4 1003.20   704.3 1005.46   792.0 1010.01   835.3 1015.89   880.5 1018.27
   930.6 1022.70   954.4 1023.34   978.2 1025.67  1049.7 1028.56  1114.6 1032.49
#Mann= 3 , 0 , 0
       0     0.1       0   630.8   0.045       0   645.8     0.1       0
Bank Sta=   630.8,   645.8
Exp/Cntr=0.3,0.1

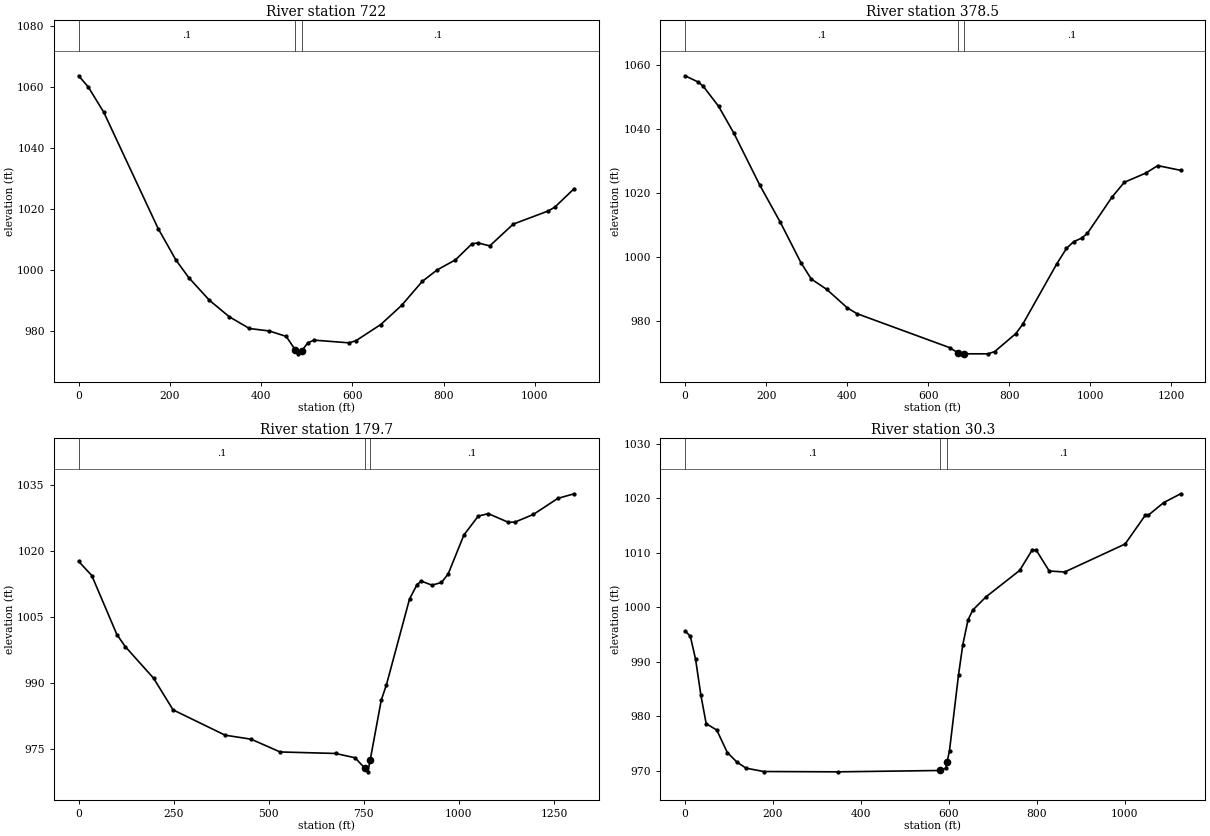
Type RM Length L Ch R = 1 ,722,337.581,343.497,344.251
XS GIS Cut Line= 3
     1763235.881      284670.538     1762844.157      284951.244
     1762285.890      285182.171
#Sta/Elev= 30
       0 1063.71    21.1 1060.05    55.1 1051.76   174.2 1013.69   213.6 1003.28
   241.6  997.56   286.6  990.19   330.4  984.76   374.3  980.94   418.1  980.12
   455.0  978.34   474.4  974.03   480.6  972.64   489.4  973.71   502.8  976.33
   516.8  977.12   592.8  976.24   607.7  976.93   662.2  982.24   707.7  988.48
   753.1  996.36   785.5 1000.10   825.8 1003.42   862.2 1008.68   875.4 1008.97
   901.1 1007.99   952.5 1015.12  1029.6 1019.45  1044.0 1020.73  1086.1 1026.75
#Mann= 3 , 0 , 0
       0     0.1       0   474.4   0.045       0   489.4     0.1       0
Bank Sta=   474.4,   489.4
Exp/Cntr=0.3,0.1

Type RM Length L Ch R = 1 ,378.5,208.804,198.81,183.544
XS GIS Cut Line= 3
     1763270.079      284447.576     1762633.706      284690.685
     1762267.934      285090.310
#Sta/Elev= 30
       0 1056.74    31.8 1054.82    44.5 1053.52    82.7 1047.19   120.7 1038.72
   184.3 1022.57   235.2 1010.91   286.0  998.31   311.4  993.22   349.6  989.98
   400.4  984.20   424.3  982.39   653.2  971.76   673.1  970.18   683.8  969.84
   688.1  969.85   748.1  969.84   764.2  970.56   816.2  976.16   833.0  979.03
   917.0  997.89   941.3 1002.80   959.1 1004.90   978.5 1006.00   992.7 1007.47
  1054.0 1018.89  1084.0 1023.46  1136.7 1026.31  1166.6 1028.66  1223.0 1027.19
#Mann= 3 , 0 , 0
       0     0.1       0   673.1   0.045       0   688.1     0.1       0
Bank Sta=   673.1,   688.1
Exp/Cntr=0.3,0.1

Type RM Length L Ch R = 1 ,179.7,165.163,149.346,149.368
XS GIS Cut Line= 3
     1763015.927      284140.094     1762468.179      284668.906
     1762102.407      285068.530
#Sta/Elev= 30
       0 1017.65    34.6 1014.42   100.6 1001.04   122.8  998.28   197.1  991.13
   248.4  983.94   385.2  978.20   453.5  977.29   529.7  974.39   675.8  974.05
   727.0  973.07   751.9  970.77   760.7  969.88   766.9  972.66   795.8  986.15
   809.5  989.66   870.2 1009.12   890.0 1012.39   901.4 1013.16   929.0 1012.24
   954.1 1012.85   971.7 1014.77  1013.1 1023.62  1050.9 1027.92  1077.2 1028.47
  1130.0 1026.51  1147.5 1026.56  1195.8 1028.29  1260.2 1031.94  1303.1 1032.98
#Mann= 3 , 0 , 0
       0     0.1       0   751.9   0.045       0   766.9     0.1       0
Bank Sta=   751.9,   766.9
Exp/Cntr=0.3,0.1

Type RM Length L Ch R = 1 ,30.3,16.352,30.346,29.856
XS GIS Cut Line= 3
     1762472.936      283968.418     1762381.060      284546.938
     1762015.288      284946.563
#Sta/Elev= 30
       0  995.66    11.9  994.67    23.9  990.43    36.0  983.80    48.0  978.62
    72.0  977.46    96.1  973.32   117.8  971.58   138.5  970.46   178.8  969.84
   348.5  969.78   581.1  970.03   593.2  970.46   596.1  971.57   601.6  973.69
   622.2  987.63   631.9  993.13   643.7  997.65   654.4  999.47   684.7 1001.91
   761.3 1006.76   790.2 1010.58   799.3 1010.43   828.5 1006.65   863.7 1006.47
  1001.2 1011.61  1047.0 1016.88  1053.9 1016.90  1089.0 1019.21  1127.5 1020.83
#Mann= 3 , 0 , 0
       0     0.1       0   581.1   0.045       0   596.1     0.1       0
Bank Sta=   581.1,   596.1
Exp/Cntr=0.3,0.1